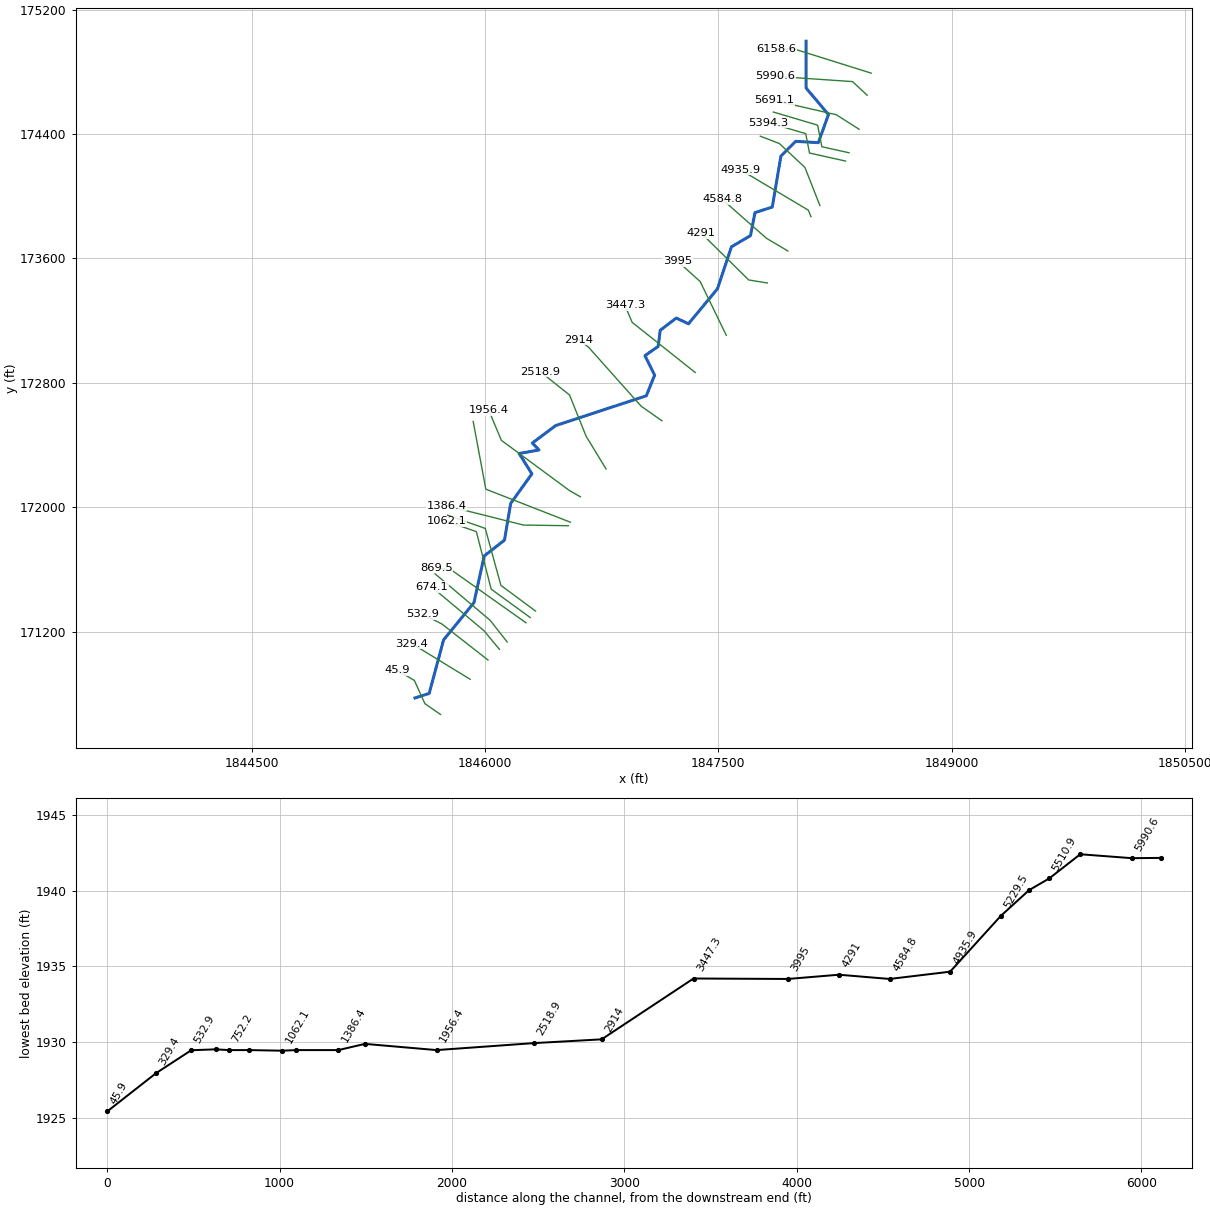
--- BEAVERCK1.prj (project) ---

Proj Title=BEAVERCK1
Current Plan=p01
Default Exp/Contr=0,0
English Units
Geom File=g01
Flow File=f01
Plan File=p01
BEGIN DESCRIPTION:
END DESCRIPTION:
DSS Export Rating Curves= 0
DSS Export Rating Curve Sorted= 0
DSS Export Volume Flow Curves= 0
DXF OffsetX= 0
DXF OffsetY= 0
DXF ScaleX= 0
DXF ScaleY= 0

--- BEAVERCK1.p01 (plan) ---

Plan Title=Floodplain
Program Version=4.00
Geom File=g01
Flow File=f01
K Sum by GR=0
Std Step Tol=0.01
Critical Tol=0.01
Num of Std Step Trials=20
Max Error Tol=0.3
Flow Tol Ratio=0.001
Split Flow NTrial=30
Split Flow Tol=0.02
Split Flow Ratio=0.02
Log Output Level=0
Friction Slope Method=1
Unsteady Friction Slope Method=2
Unsteady Bridges Friction Slope Method=1
Global Log Level=0
CheckData=False
Run HTab=0
Run UNet=0
Run PostProcess=0
UNET Theta=0
UNET Theta Warmup=0
UNET ZTol=0
UNET ZSATol=0
UNET MxIter=0
UNET MaxInSteps=0
UNET DtIC=0
UNET DtMin=0
UNET MaxCRTS=0
UNET WFStab=0
UNET SFStab=0
UNET WFX=0
UNET SFX=0
UNET DSS MLevel=0
UNET DZMax Abort=0
UNET Convert EG Bridges=0
UNET Use Existing IB Tables=0
UNET Froude Limit=0
UNET Froude Power=0
Write IC File=0
Echo Input=False
Echo Output=False
Write Detailed=0

--- BEAVERCK1.f01 (steady flow) ---

Flow Title=NFF Regression Equation
Program Version=4.10
Number of Profiles= 1
Profile Names=P100yr
River Rch & RM=BEAVERCK1,Main            ,6158.6
470.3788
River Rch & RM=BEAVERCK1,Main            ,5990.6
814.9551
River Rch & RM=BEAVERCK1,Main            ,3995
836.0434
River Rch & RM=BEAVERCK1,Main            ,45.9
928.3897
Boundary for River Rch & Prof#=BEAVERCK1,Main            , 1
Up Type= 0
Dn Type= 3
Dn Slope=0.008
DSS Import GetInterval= 0
DSS Import GetPeak= 0
DSS Import FillOption= 0

--- BEAVERCK1.g01 (geometry) ---

Geom Title=USGS 10m DEM
Program Version=4.10

River Reach=BEAVERCK1       ,Main
Reach XY= 30
     1848064.834      174996.589     1848064.741      174695.864
     1848208.668      174525.111     1848143.443      174344.292
     1847998.043      174352.973     1847902.975      174258.033
     1847847.436       173930.23     1847736.325      173894.639
     1847707.245      173746.636     1847585.009       173674.71
     1847495.324      173405.282     1847308.582      173179.666
     1847230.091      173216.668      1847127.05      173138.067
     1847113.552      173034.197     1847028.859      172974.935
     1847090.925      172849.935      1847037.54      172716.688
     1846454.129      172525.189     1846304.672      172412.841
     1846347.504      172368.188     1846219.859        172345.8
     1846301.722      172214.807     1846165.297      172024.397
     1846125.682      171789.007     1845995.005       171686.74
     1845929.405      171386.779     1845734.025      171147.285
     1845641.302      170802.943      1845550.37      170774.178

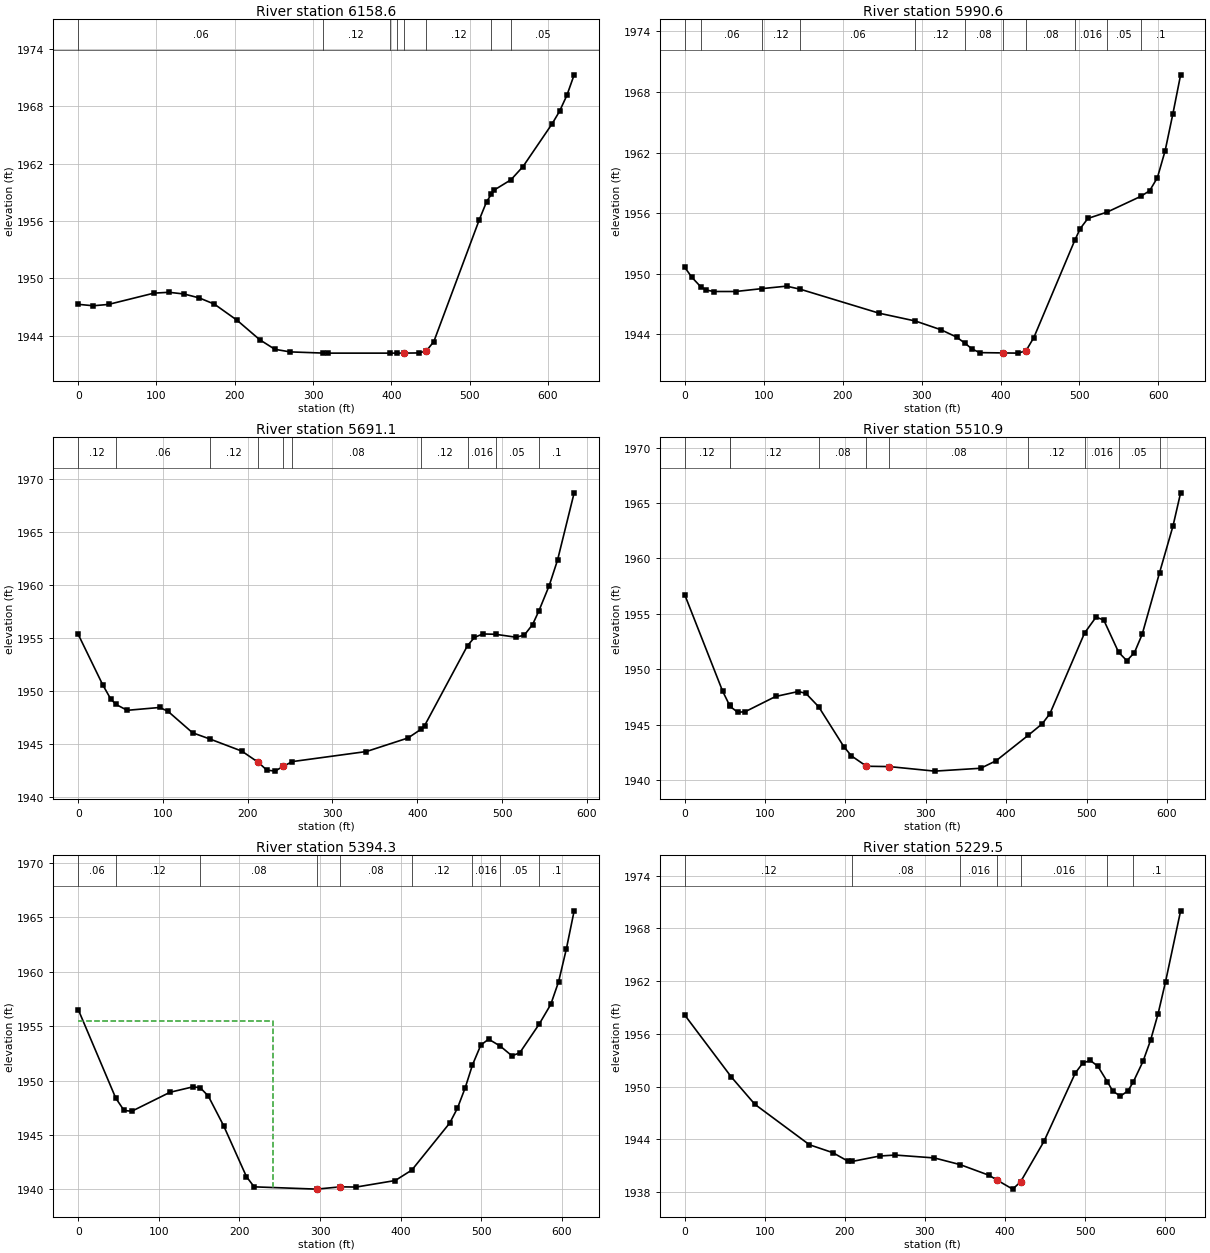
Type RM Length L Ch R = 1 ,6158.6  ,158.8,168,183.7
XS GIS Cut Line= 3
     1848483.414      174791.351     1847994.548      174944.691
     1847873.229      174947.009
#Sta/Elev= 30
       0 1947.27    19.3 1947.12    38.7 1947.26    96.7 1948.44     116 1948.53
   135.3 1948.35   154.7 1947.94     174 1947.29     203  1945.6     232 1943.56
   251.3 1942.56   270.7 1942.29   312.31942.167     319 1942.16  398.01 1942.16
  407.73 1942.16   415.7 1942.16     435 1942.18   444.7 1942.38   454.4 1943.37
   512.4 1956.11   521.7 1957.99  528.081958.827     531 1959.21  552.891960.307
   568.4  1961.7   605.7 1966.19     615 1967.48   624.4 1969.15   633.7  1971.3
#Mann= 8 ,-1 , 0
       0     .06       0   312.3     .12       0  398.01     .08       0
  407.73     .12       0   415.7    .045       0   444.7     .12       0
  528.08    .016       0  552.89     .05       0
Bank Sta=415.7,444.7
XS Rating Curve= 0 ,0
Exp/Cntr=0.3,0.1

Type RM Length L Ch R = 1 ,5990.6  ,304.9,299.5,291.7
XS GIS Cut Line= 3
     1848457.567      174649.194     1848363.095      174737.023
     1847865.156      174771.003
#Sta/Elev= 30
       0 1950.64     9.2 1949.64    20.61948.684    27.6 1948.38    36.8 1948.24
    64.5 1948.24   97.551948.523     129 1948.77  146.311948.467   246.4 1946.09
  292.321945.316   324.7 1944.45   344.3 1943.73  355.371943.098   363.9 1942.55
   373.6 1942.19     403 1942.16   422.6 1942.14   432.4 1942.39   442.2 1943.68
  494.091953.313   500.9 1954.46   510.6 1955.47  535.171956.107  577.761957.663
   588.9 1958.22   598.7 1959.51   608.5 1962.18   618.3 1965.83   628.1 1969.69
#Mann= 11 ,-1 , 0
       0     .12       0    20.6     .06       0   97.55     .12       0
  146.31     .06       0  292.32     .12       0  355.37     .08       0
     403    .045       0   432.4     .08       0  494.09    .016       0
  535.17     .05       0  577.76      .1       0
Bank Sta=403,432.4
XS Rating Curve= 0 ,0
Exp/Cntr=0.3,0.1

Type RM Length L Ch R = 1 ,5691.1  ,239.5,180.2,105.4
XS GIS Cut Line= 3
      1848405.59      174430.593     1848259.305      174523.684
     1847858.043      174615.952
#Sta/Elev= 30
       0 1955.31    28.9 1950.55    38.5 1949.19   44.711948.691    57.8 1948.14
    96.3 1948.41     106 1948.04   134.9 1946.02  154.951945.444     193 1944.29
   212.6 1943.22   222.4  1942.5   232.2  1942.4     242 1942.86  252.63  1943.3
     340 1944.25   389.1 1945.53  404.961946.379   408.7  1946.7   459.3 1954.25
   467.5 1955.02   477.3 1955.35  492.341955.317   516.5 1955.04   526.3 1955.24
   536.1 1956.24  543.661957.559   555.7 1959.92   565.5 1962.32   585.1 1968.67
#Mann= 10 ,-1 , 0
       0     .12       0   44.71     .06       0  154.95     .12       0
   212.6    .045       0     242     .12       0  252.63     .08       0
  404.96     .12       0   459.3    .016       0  492.34     .05       0
  543.66      .1       0
Bank Sta=212.6,242
XS Rating Curve= 0 ,0
Exp/Cntr=0.3,0.1

Type RM Length L Ch R = 1 ,5510.9  ,100.2,116.6,138.2
XS GIS Cut Line= 4
     1848341.039      174279.359     1848166.206      174318.172
     1848138.934       174456.93     1847854.615      174541.204
#Sta/Elev= 30
       0 1956.74    47.1 1948.04   55.911946.732   56.461946.651      66 1946.11
    75.4 1946.17   113.1 1947.54   141.4 1947.99   150.8 1947.82  166.691946.611
   197.9 1943.02   207.4 1942.18   226.2 1941.24   254.5 1941.21   311.1  1940.8
   368.3 1941.06   387.5 1941.74  427.721944.054   444.9 1945.08   454.4 1945.99
  497.491953.269   511.8 1954.71   521.4 1954.44  539.841951.534   550.1 1950.77
   559.6 1951.51   569.2 1953.16  590.781958.716   607.5 1962.93     617 1965.93
#Mann= 10 ,-1 , 0
       0     .12       0   55.91     .06       0   56.46     .12       0
  166.69     .08       0   226.2    .045       0   254.5     .08       0
  427.72     .12       0  497.49    .016       0  539.84     .05       0
  590.78      .1       0
Bank Sta=226.2,254.5
XS Rating Curve= 0 ,0
Exp/Cntr=0.3,0.1

Type RM Length L Ch R = 1 ,5394.3  ,143,164.7,187.2
XS GIS Cut Line= 4
     1848318.326      174226.144     1848086.779      174277.547
     1848062.546       174402.33     1847821.948      174473.029
#Sta/Elev= 30
       0 1956.52   46.621948.377    56.9 1947.25    66.4 1947.18   113.8 1948.92
   142.3 1949.42  151.241949.345   161.3 1948.58   180.3 1945.86   208.7 1941.17
   218.2 1940.24   295.8 1940.03   325.2 1940.24   344.7 1940.22   393.2 1940.82
  413.791941.781   460.8  1946.1   470.4 1947.47     480 1949.34  488.961951.428
   499.3 1953.25     509  1953.8  523.491953.157   537.9 1952.27   547.6 1952.54
  571.721955.177   586.1 1956.99   595.8 1959.07   605.4 1962.07   615.1 1965.58
#Mann= 9 ,-1 , 0
       0     .06       0   46.62     .12       0  151.24     .08       0
   295.8    .045       0   325.2     .08       0  413.79     .12       0
  488.96    .016       0  523.49     .05       0  571.72      .1       0
#XS Ineff= 2 , 0
          240.98  1955.5
Permanent Ineff=
       F       F
Bank Sta=295.8,325.2
XS Rating Curve= 0 ,0
Exp/Cntr=0.3,0.1

Type RM Length L Ch R = 1 ,5229.5  ,283.8,293.7,300.2
XS GIS Cut Line= 4
     1848153.556      173940.232     1848057.323      174184.939
      1847893.26      174338.585     1847770.622       174385.93
#Sta/Elev= 30
       0 1958.15    58.4 1951.07    87.6 1947.98   155.8 1943.37     185 1942.47
   204.5 1941.47  209.271941.475   243.5 1942.09     263  1942.2   311.8 1941.87
  343.921941.111   380.2 1939.89     390 1939.35   409.5 1938.32   419.3 1939.14
   448.6 1943.76   487.7 1951.54   497.1 1952.68   506.5 1952.97   515.9 1952.31
  527.581950.566   534.7 1949.46   544.1 1948.91   553.4 1949.51  559.931950.496
   572.2 1952.86   581.6 1955.25     591 1958.26   600.4 1961.95   619.2 1970.01
#Mann= 7 ,-1 , 0
       0     .12       0  209.27     .08       0  343.92    .016       0
     390    .045       0   419.3    .016       0  527.58     .05       0
  559.93      .1       0
Bank Sta=390,419.3
XS Rating Curve= 0 ,0
Exp/Cntr=0.3,0.1

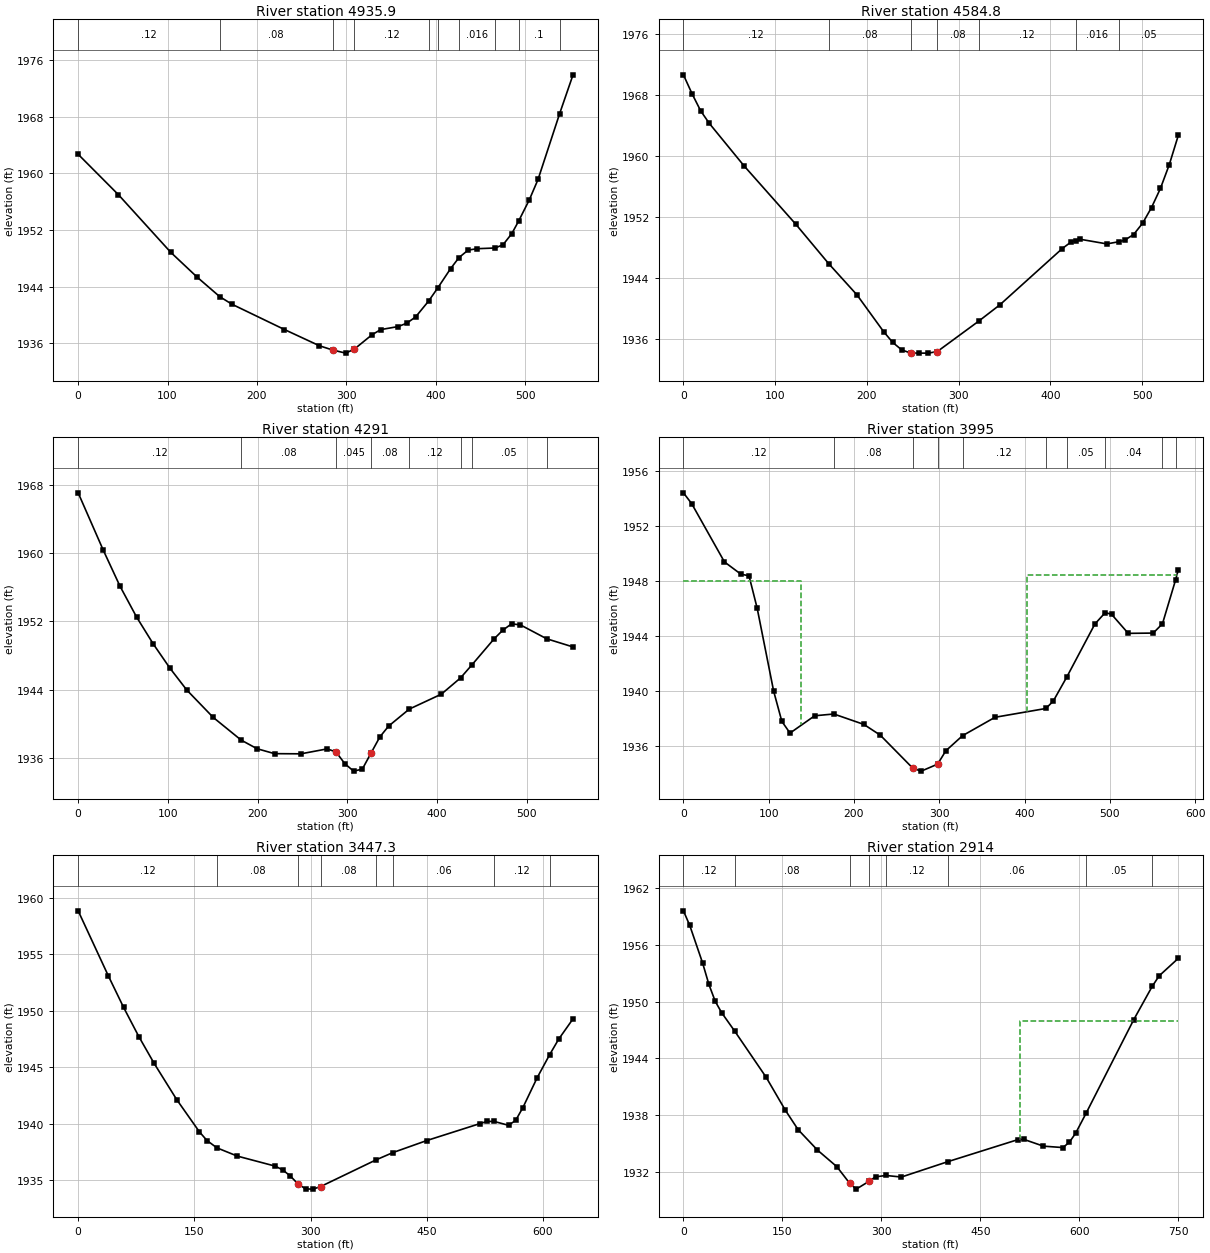
Type RM Length L Ch R = 1 ,4935.9  ,352.8,351.1,325.2
XS GIS Cut Line= 3
     1848096.044      173868.731     1848079.183      173910.402
     1847642.077      174170.488
#Sta/Elev= 30
       0 1962.71      45 1957.01   103.6 1948.87     133 1945.38  158.431942.607
   172.1 1941.54   230.8 1937.97   269.9 1935.68   284.7 1935.08   299.3 1934.64
     309 1935.21   328.6 1937.22   338.4 1937.96     358 1938.39   367.7 1938.87
   377.5 1939.75  392.021941.984  402.351943.856   416.6 1946.56  426.061948.133
   436.2 1949.18     446 1949.38  466.431949.483   475.3 1949.94   485.1 1951.51
  492.721953.275   504.7 1956.28   514.5 1959.17  538.541968.418   553.6 1973.93
#Mann= 10 ,-1 , 0
       0     .12       0  158.43     .08       0   284.7    .045       0
     309     .12       0  392.02     .06       0  402.35      .1       0
  426.06    .016       0  466.43     .05       0  492.72      .1       0
  538.54     .05       0
Bank Sta=284.7,309
XS Rating Curve= 0 ,0
Exp/Cntr=0.3,0.1

Type RM Length L Ch R = 1 ,4584.8  ,287.6,293.8,302.6
XS GIS Cut Line= 3
     1847947.826      173647.893     1847810.086      173729.413
      1847525.15      173979.941
#Sta/Elev= 30
       0 1970.62     9.4 1968.14    18.8  1965.9    28.2 1964.26    65.9 1958.72
   122.4 1951.06  158.431945.872   189.2 1941.79   218.4 1936.95   228.2 1935.56
   237.9 1934.59   247.6 1934.17   257.3 1934.16   267.1 1934.16   276.8 1934.37
  321.721938.333   344.9 1940.48     413 1947.86   422.7 1948.73  427.591948.906
   432.4 1949.08   461.6 1948.47  475.121948.763   481.1 1948.96   490.8  1949.7
   500.6 1951.18   510.3 1953.23     520 1955.73   529.7 1958.86   539.5 1962.68
#Mann= 7 ,-1 , 0
       0     .12       0  158.43     .08       0   247.6    .045       0
   276.8     .08       0  321.72     .12       0  427.59    .016       0
  475.12     .05       0
Bank Sta=247.6,276.8
XS Rating Curve= 0 ,0
Exp/Cntr=0.3,0.1

Type RM Length L Ch R = 1 ,4291    ,308.5,295.9,282.6
XS GIS Cut Line= 3
     1847815.421      173442.054     1847695.995      173461.632
     1847389.405      173763.646
#Sta/Elev= 30
       0 1967.09    27.9 1960.38    46.6 1956.14    65.2  1952.5    83.8 1949.34
   102.4  1946.5     121 1943.96   150.4 1940.75   181.61938.082   199.3 1937.07
   218.8 1936.49   248.2 1936.47   277.5 1937.05   287.3 1936.69   297.1 1935.32
   306.9 1934.44   316.6 1934.67   326.4 1936.57   336.2 1938.46     346 1939.73
  368.941941.717   404.7 1943.47  426.041945.374  438.731946.903   463.4 1949.95
   473.1 1950.97   482.9 1951.72   492.7  1951.6  522.071949.967   551.4 1949.01
#Mann= 8 ,-1 , 0
       0     .12       0   181.6     .08       0   287.3    .045       0
   326.4     .08       0  368.94     .12       0  426.04     .06       0
  438.73     .05       0  522.07    .016       0
Bank Sta=287.3,326.4
XS Rating Curve= 0 ,0
Exp/Cntr=0.3,0.1

Type RM Length L Ch R = 1 ,3995    ,525.1,547.7,521.6
XS GIS Cut Line= 3
     1847551.897      173105.512     1847383.712      173451.433
     1847238.399       173582.44
#Sta/Elev= 30
       0 1954.42     9.6 1953.64    48.1 1949.39    67.3  1948.5    76.9 1948.38
    86.5 1946.01   105.8 1939.98   115.4 1937.78     125 1936.93   153.9 1938.19
  176.351938.319   211.6 1937.56   230.8 1936.78   269.2 1934.36   278.9 1934.16
   298.1 1934.67   307.7 1935.64  327.29 1936.74   365.4 1938.08  424.95 1938.72
   433.6 1939.25   449.51941.005   482.5 1944.87  494.62  1945.7     502 1945.58
   521.6 1944.19   550.9 1944.21  561.75 1944.89  577.061948.066   580.3 1948.81
#Mann= 10 ,-1 , 0
       0     .12       0  176.35     .08       0   269.2    .045       0
   298.1     .08       0  327.29     .12       0  424.95     .06       0
   449.5     .05       0  494.62     .04       0  561.75     .05       0
  577.06    .016       0
#XS Ineff= 2 , 0
           137.7 1947.98  403.28         1948.46
Permanent Ineff=
       F       F
Bank Sta=269.2,298.1
XS Rating Curve= 0 ,0
Exp/Cntr=0.3,0.1

Type RM Length L Ch R = 1 ,3447.3  ,527.5,533.2,529.6
XS GIS Cut Line= 3
     1847351.986      172866.558     1846946.212       173189.28
     1846899.362      173300.061
#Sta/Elev= 30
       0 1958.87    39.1 1953.08    58.7  1950.3    78.3 1947.72    97.8 1945.37
   127.2 1942.13   156.5 1939.27   166.3  1938.5  179.051937.852   205.4 1937.12
   254.3 1936.23   264.1 1935.89   273.9 1935.35   283.7 1934.65   293.5 1934.21
   303.2 1934.19     313 1934.42  384.781936.794  406.261937.432     450  1938.5
   518.5    1940   527.7 1940.19  536.531940.199   555.5 1939.85   564.7 1940.29
     574 1941.42   592.5 1944.08  608.651946.127   620.2 1947.49   638.7 1949.29
#Mann= 8 ,-1 , 0
       0     .12       0  179.05     .08       0   283.7    .045       0
     313     .08       0  384.78     .12       0  406.26     .06       0
  536.53     .12       0  608.65      .1       0
Bank Sta=283.7,313
XS Rating Curve= 0 ,0
Exp/Cntr=0.3,0.1

Type RM Length L Ch R = 1 ,2914    ,414.7,395.1,378.3
XS GIS Cut Line= 4
      1847138.09      172555.813     1847003.937      172650.217
     1846665.396      173029.992     1846603.478        173076.3
#Sta/Elev= 30
       0 1959.63     9.6 1958.08      29 1954.12    38.6 1951.84    48.2 1950.05
    57.9 1948.85   77.611946.904   125.4 1942.01   154.4 1938.53   173.8 1936.47
   203.2  1934.3   232.5 1932.55   252.1 1930.78   261.9 1930.17   281.4    1931
   291.2 1931.47   306.91931.616   330.4 1931.45  401.311933.089   506.5  1935.4
   516.3 1935.43   545.6 1934.72     575 1934.57   584.8 1935.11   594.5 1936.09
  610.341938.203   682.5  1948.1  710.481951.623   721.1 1952.75   750.1  1954.6
#Mann= 8 ,-1 , 0
       0     .12       0   77.61     .08       0   252.1    .045       0
   281.4     .08       0   306.9     .12       0  401.31     .06       0
  610.34     .05       0  710.48    .016       0
#XS Ineff= 2 , 0
                          509.46         1947.98
Permanent Ineff=
       F       F
Bank Sta=252.1,281.4
XS Rating Curve= 0 ,0
Exp/Cntr=0.3,0.1

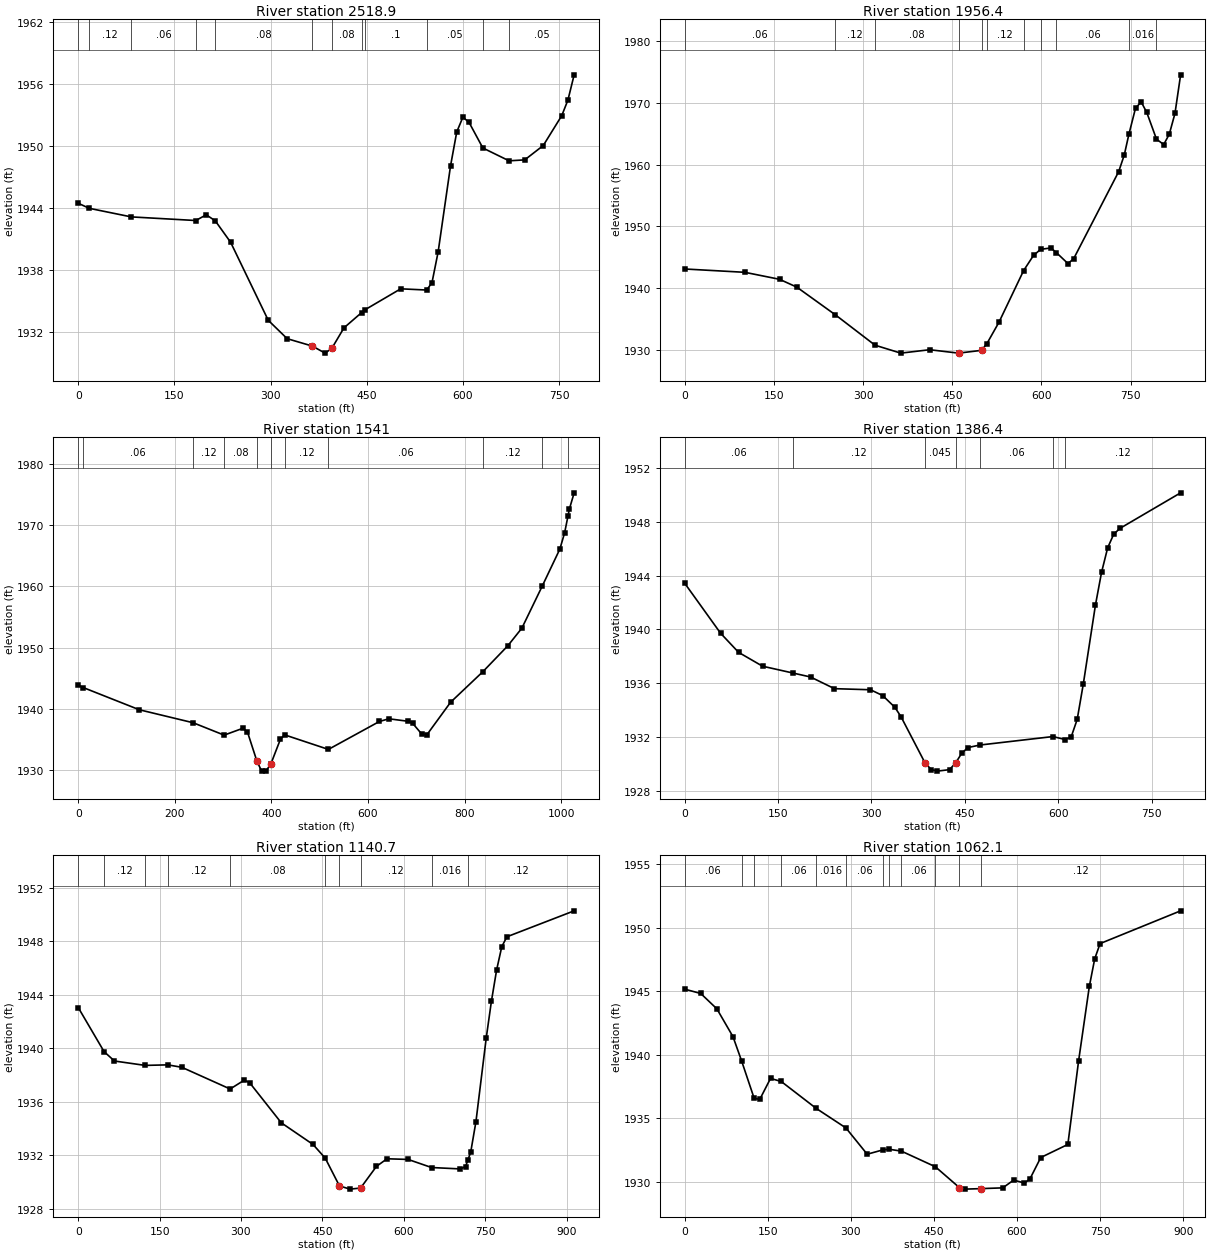
Type RM Length L Ch R = 1 ,2518.9  ,532.2,562.6,518.2
XS GIS Cut Line= 4
     1846778.884      172245.996     1846650.205      172457.075
     1846543.868      172721.832     1846355.441      172872.034
#Sta/Elev= 30
       0 1944.44   17.141943.949   82.751943.117  183.381942.766   199.7 1943.32
  213.761942.736   237.7 1940.66   296.4  1933.1   325.9 1931.32   365.3  1930.6
     385 1929.92   395.4 1930.37   414.5 1932.37   441.91933.842  447.871934.141
     503 1936.15  543.581936.032   551.8 1936.76   561.4 1939.74   580.7 1948.06
   590.4 1951.35     600 1952.78   609.6 1952.27  631.121949.792     672 1948.55
   696.4 1948.64   725.3 1950.03   754.2 1952.93   763.8 1954.44   773.5 1956.88
#Mann= 12 ,-1 , 0
       0    .016       0   17.14     .12       0   82.75     .06       0
  183.38     .12       0  213.76     .08       0   365.3    .045       0
   395.4     .08       0   441.9     .12       0  447.87      .1       0
  543.58     .05       0  631.12    .016       0     672     .05       0
Bank Sta=365.3,395.4
XS Rating Curve= 0 ,0
Exp/Cntr=0.3,0.1

Type RM Length L Ch R = 1 ,1956.4  ,278.5,415.4,428.7
XS GIS Cut Line= 4
     1846613.835      172067.358     1846542.783        172107.9
     1846105.283      172430.816     1846024.896      172623.093
#Sta/Elev= 30
       0 1943.09   101.2 1942.55   159.5 1941.42   188.6 1940.15  253.621935.649
  320.051930.746   363.4 1929.46     412 1930.01   460.5 1929.46   499.3 1929.91
  508.331931.018   528.5 1934.46  569.981942.832   586.7  1945.3  598.691946.271
   615.9  1946.5     6251945.749   644.5 1943.97     654 1944.73   729.8 1958.85
   739.2 1961.54  746.94 1964.88   758.2 1969.16   767.7 1970.15   777.1 1968.44
  793.431964.115   805.6 1963.25     815 1964.94   824.5 1968.29     834 1974.54
#Mann= 11 ,-1 , 0
       0     .06       0  253.62     .12       0  320.05     .08       0
   460.5    .045       0   499.3     .08       0  508.33     .12       0
  569.98     .06       0  598.69     .12       0     625     .06       0
  746.94    .016       0  793.43     .12       0
Bank Sta=460.5,499.3
XS Rating Curve= 0 ,0
Exp/Cntr=0.3,0.1

Type RM Length L Ch R = 1 ,1541    ,152,154.6,154.9
XS GIS Cut Line= 3
     1846549.839      171903.747     1846005.673      172116.363
     1845924.397      172551.505
#Sta/Elev= 30
       0 1943.86   10.73 1943.48   126.6 1939.87  237.861937.759  302.161935.737
   340.8 1936.85   350.5 1936.24     370  1931.5   379.8 1929.87   389.5 1929.96
   399.2  1931.1   418.7 1935.07  427.341935.783  518.07 1933.41   623.6 1937.96
   643.2  1938.4   682.6    1938   692.4 1937.67   712.1 1935.84     722  1935.8
   771.1  1941.1  837.821946.073   889.2 1950.27   918.7 1953.18  960.881960.041
   997.4 1966.08  1007.2 1968.73 1014.131971.446  1017.1 1972.61  1026.9 1975.23
#Mann= 11 ,-1 , 0
       0    .016       0   10.73     .06       0  237.86     .12       0
  302.16     .08       0     370    .045       0   399.2     .08       0
  427.34     .12       0  518.07     .06       0  837.82     .12       0
  960.88     .06       0 1014.13    .016       0
Bank Sta=370,399.2
XS Rating Curve= 0 ,0
Exp/Cntr=0.3,0.1

Type RM Length L Ch R = 1 ,1386.4  ,281.2,245.7,203.1
XS GIS Cut Line= 3
     1846536.068      171881.382     1846247.439      171885.722
     1845754.818       172009.42
#Sta/Elev= 30
       0 1943.43    57.7 1939.71    86.6 1938.29   125.1 1937.26   173.2 1936.76
   202.1 1936.46   240.6 1935.59   298.4 1935.51     318 1935.08   337.5 1934.21
   347.3 1933.52   386.3 1930.05   396.1 1929.58   405.9 1929.46   425.4 1929.57
   435.2 1930.07   444.9 1930.78   454.7 1931.21   474.2  1931.4   591.5 1932.03
     611 1931.81   620.8    1932   630.5 1933.31   640.3 1935.94   659.8 1941.81
   669.6 1944.24   679.4 1946.06   689.1 1947.07   698.9  1947.5   796.6 1950.15
#Mann= 7 ,-1 , 0
       0     .06       0   173.2     .12       0   386.3    .045       0
   435.2     .12       0   474.2     .06       0   591.5    .016       0
     611     .12       0
Bank Sta=386.3,435.2
XS Rating Curve= 0 ,0
Exp/Cntr=0.3,0.1

Type RM Length L Ch R = 1 ,1140.7  ,102.9,78.6,67.8
XS GIS Cut Line= 4
     1846325.171      171332.806     1846102.679      171497.656
     1846001.984      171863.976     1845759.229      171949.313
#Sta/Elev= 30
       0 1943.04   47.721939.739    66.8 1939.04  123.361938.712  165.111938.752
     191 1938.57  280.031936.947   306.1 1937.61   315.9 1937.42   374.3 1934.42
   432.8  1932.8  455.321931.775   481.5  1929.7     501 1929.46   520.4 1929.54
   549.7 1931.16   569.2 1931.73   608.1 1931.68  651.211931.076   704.5 1930.97
     714 1931.15  718.491931.665   723.5 1932.24   733.1 1934.51   752.1 1940.78
   761.6 1943.51   771.2 1945.85   780.7 1947.59   790.2 1948.33   914.1 1950.27
#Mann= 10 ,-1 , 0
       0     .06       0   47.72     .12       0  123.36    .016       0
  165.11     .12       0  280.03     .08       0  455.32     .12       0
   481.5    .045       0   520.4     .12       0  651.21    .016       0
  718.49     .12       0
Bank Sta=481.5,520.4
XS Rating Curve= 0 ,0
Exp/Cntr=0.3,0.1

Type RM Length L Ch R = 1 ,1062.1  ,142.3,192.6,230.7
XS GIS Cut Line= 4
     1846290.825        171291.1     1846040.179      171473.351
     1845944.693      171843.143     1845752.596      171910.671
#Sta/Elev= 30
       0 1945.17      29 1944.83    58.1 1943.62    87.2 1941.43   102.71939.528
  125.421936.574   135.6 1936.49     155 1938.14  174.351937.898  237.371935.781
  291.12 1934.24   329.5 1932.17  358.54 1932.52  369.411932.558  391.251932.413
  452.531931.184     496 1929.54   505.8 1929.42   535.1 1929.46   574.3 1929.52
   593.9 1930.13   613.5  1929.9   623.3 1930.22   642.9 1931.91   691.8 1932.94
   711.2 1939.52   730.6 1945.39   740.3 1947.56     750 1948.76   895.4 1951.34
#Mann= 12 ,-1 , 0
       0     .06       0   102.7     .12       0  125.42    .016       0
  174.35     .06       0  237.37    .016       0  291.12     .06       0
  358.54    .016       0  369.41     .12       0  391.25     .06       0
  452.53    .016       0     496    .045       0   535.1     .12       0
Bank Sta=496,535.1
XS Rating Curve= 0 ,0
Exp/Cntr=0.3,0.1

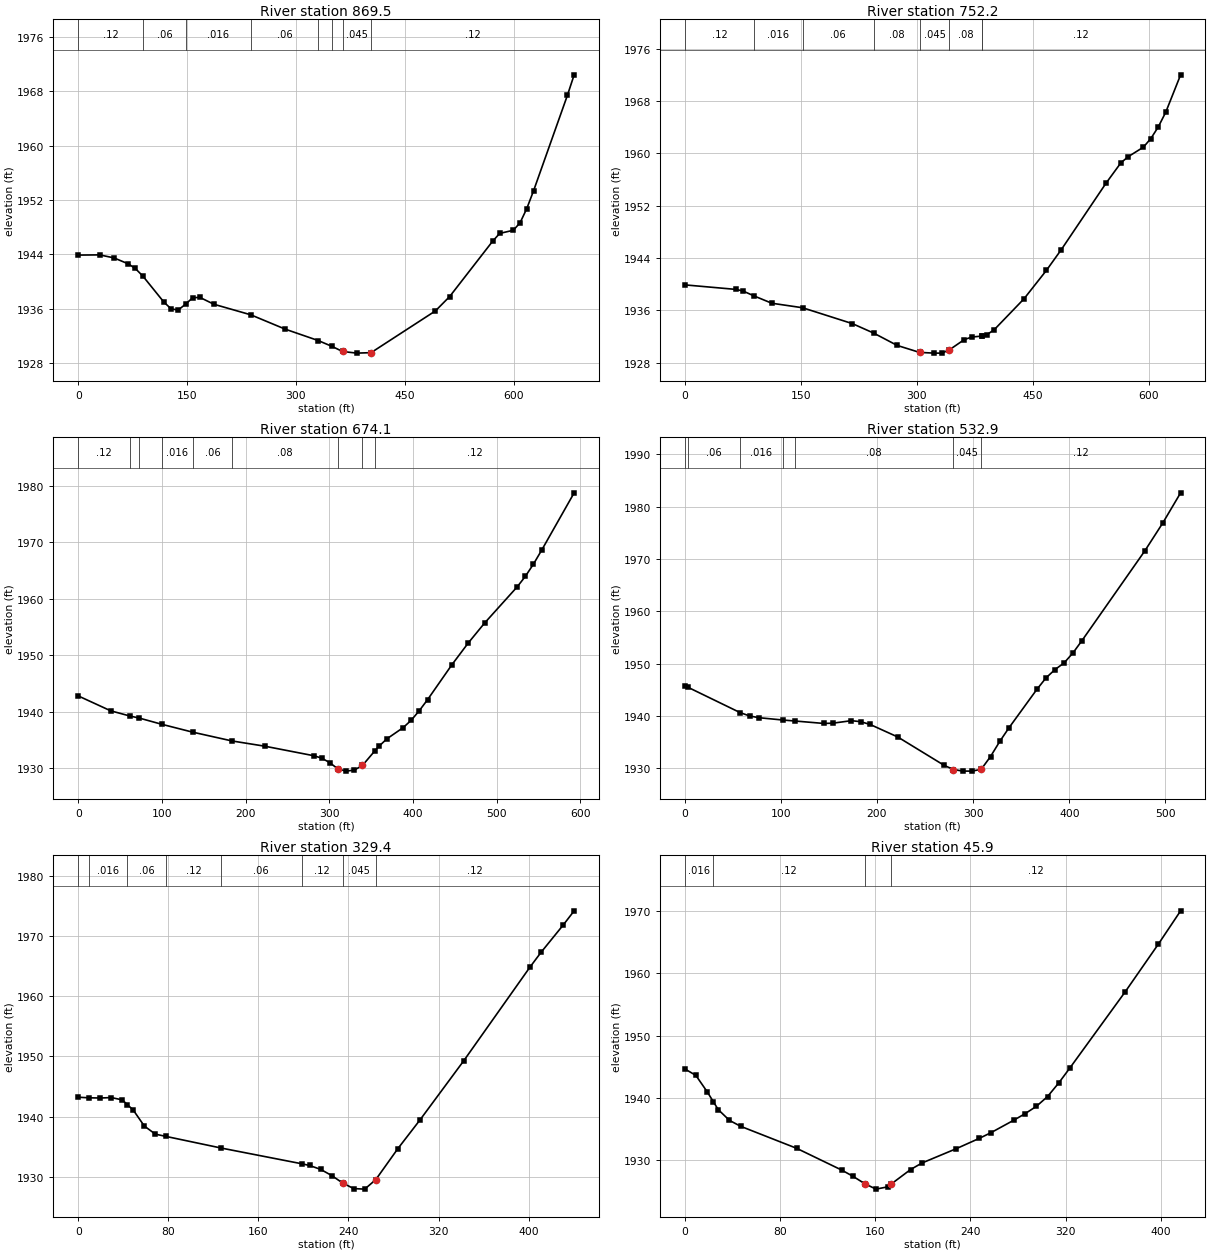
Type RM Length L Ch R = 1 ,869.5   ,119.2,117.2,113.3
XS GIS Cut Line= 3
     1846263.378      171257.771     1845789.311      171593.143
     1845688.486      171612.047
#Sta/Elev= 30
       0 1943.89    29.5 1943.92    49.2 1943.48    68.9  1942.6    78.7 1941.92
   89.351940.763   118.1 1936.96     128 1935.98   137.8  1935.8   148.11936.688
   157.5 1937.59   167.3 1937.68     187 1936.65  237.77  1935.1   285.4 1932.98
  330.741931.308  349.921930.439   364.2  1929.7   383.8 1929.46   403.5 1929.53
   492.1 1935.67   511.8 1937.79   570.9 1945.92   580.7 1947.08   599.4 1947.54
   608.7 1948.63     618 1950.73   627.3 1953.33     674  1967.4   683.3 1970.42
#Mann= 8 ,-1 , 0
       0     .12       0   89.35     .06       0   148.1    .016       0
  237.77     .06       0  330.74     .08       0  349.92     .12       0
   364.2    .045       0   403.5     .12       0
Bank Sta=364.2,403.5
XS Rating Curve= 0 ,0
Exp/Cntr=0.3,0.1

Type RM Length L Ch R = 1 ,752.2   ,77.7,78.1,78.8
XS GIS Cut Line= 3
      1846142.94      171133.796       1846032.8      171273.915
     1845678.984      171572.258
#Sta/Elev= 30
       0  1939.9    65.7 1939.21      75 1938.98   89.881938.196   112.6 1937.09
  152.37  1936.4   216.8 1933.97   244.41932.517   274.6 1930.64   303.6 1929.57
   322.8 1929.46   332.5 1929.46   342.1 1929.96   361.4 1931.53   371.1 1931.92
  383.931932.063  384.371932.077   390.4 1932.27     400 1933.03   438.6 1937.77
   467.5 1942.11   486.8 1945.29   544.6 1955.45   563.9 1958.58   573.5 1959.52
   592.8 1960.95   602.5 1962.27   612.1 1964.05   621.8 1966.31     641 1972.02
#Mann= 8 ,-1 , 0
       0     .12       0   89.88    .016       0  152.37     .06       0
   244.4     .08       0   303.6    .045       0   342.1     .08       0
  383.93     .06       0  384.37     .12       0
Bank Sta=303.6,342.1
XS Rating Curve= 0 ,0
Exp/Cntr=0.3,0.1

Type RM Length L Ch R = 1 ,674.1   ,139.7,141.2,142.5
XS GIS Cut Line= 3
     1846092.967      171086.882     1845994.172       171205.99
     1845658.649      171487.104
#Sta/Elev= 30
       0 1942.81    38.7 1940.18   61.591939.259   72.631938.902   99.951937.786
  136.551936.406   183.9 1934.84   222.8 1933.92   281.2 1932.24   290.9 1931.81
   300.7 1930.99   310.4 1929.88   320.1 1929.51   329.8 1929.69   339.6 1930.52
  354.661933.141     359 1933.87   368.8 1935.22   388.2  1937.2   397.9 1938.51
   407.6 1940.22   417.4 1942.15   446.6 1948.35     466 1952.17   485.5 1955.69
   524.4 1962.08   534.1 1963.92   543.8 1966.09   553.6 1968.55   592.5 1978.71
#Mann= 9 ,-1 , 0
       0     .12       0   61.59    .016       0   72.63     .06       0
   99.95    .016       0  136.55     .06       0   183.9     .08       0
   310.4    .045       0   339.6     .08       0  354.66     .12       0
Bank Sta=310.4,339.6
XS Rating Curve= 0 ,0
Exp/Cntr=0.3,0.1

Type RM Length L Ch R = 1 ,532.9   ,199.1,203.6,207.8
XS GIS Cut Line= 3
      1846019.49      171017.903     1845723.338      171249.393
     1845598.834      171313.269
#Sta/Elev= 30
       0 1945.77    3.351945.491   57.531940.653    67.5    1940    77.1 1939.67
  102.141939.222  114.39 1939.04   144.6 1938.57   154.2 1938.62   173.5  1939.1
   183.1  1938.9   192.8 1938.38   221.7 1935.97   269.9 1930.55   279.5 1929.76
   289.2 1929.46   298.8 1929.45   308.4  1929.8   318.1 1932.24   327.7 1935.13
   337.3 1937.74   366.2 1945.06   375.9  1947.3   385.2 1948.88   394.6 1950.14
   403.9 1952.07   413.2 1954.41   478.5 1971.55   497.2 1976.89   515.8 1982.67
#Mann= 7 ,-1 , 0
       0     .12       0    3.35     .06       0   57.53    .016       0
  102.14     .06       0  114.39     .08       0   279.5    .045       0
   308.4     .12       0
Bank Sta=279.5,308.4
XS Rating Curve= 0 ,0
Exp/Cntr=0.3,0.1

Type RM Length L Ch R = 1 ,329.4   ,306.2,283.5,260.8
XS GIS Cut Line= 2
     1845904.711      170894.132     1845529.073      171123.918
#Sta/Elev= 26
       0 1943.22     9.41943.124    19.6 1943.09    29.4 1943.16    39.1 1942.78
   43.681941.985    48.9 1941.08    58.7 1938.43    68.5 1937.08   77.871936.707
  126.861934.774  198.291932.164   205.5 1931.87   215.3 1931.22   225.1  1930.2
   234.8 1928.96   244.6 1928.03   254.4 1927.94   264.2 1929.51   283.8 1934.66
   303.4 1939.42   342.5 1949.32   401.2 1964.86     411 1967.31   430.6 1971.83
   440.4 1974.21
#Mann= 8 ,-1 , 0
       0     .06       0     9.4    .016       0   43.68     .06       0
   77.87     .12       0  126.86     .06       0  198.29     .12       0
   234.8    .045       0   264.2     .12       0
Bank Sta=234.8,264.2
XS Rating Curve= 0 ,0
Exp/Cntr=0.3,0.1

Type RM Length L Ch R = 1 ,45.9    ,59.7,45.9,31.2
XS GIS Cut Line= 4
      1845714.53      170667.883     1845613.963       170737.24
     1845546.255      170886.545     1845433.945      170952.982
#Sta/Elev= 28
       0 1944.67     9.4 1943.62    18.8 1941.03    24.2 1939.37    28.2 1938.14
    37.6 1936.42      47 1935.47      94 1931.95   131.8 1928.47   141.4 1927.46
   151.1  1926.3   160.7 1925.41   170.4 1925.77   173.1 1926.17   189.7 1928.54
   199.3 1929.59   228.2 1931.89   247.5 1933.54   257.2 1934.44   276.5 1936.45
   286.1 1937.51   295.4 1938.66   304.8 1940.23   314.1 1942.38   323.4 1944.76
     370 1956.99     398 1964.67   416.6 1969.97
#Mann= 4 ,-1 , 0
       0    .016       0    24.2     .12       0   151.1    .045       0
   173.1     .12       0
Bank Sta=151.1,173.1
XS Rating Curve= 0 ,0
Exp/Cntr=0.3,0.1

Chan Stop Cuts=-1
Use User Specified Reach Order=0
Composite Channel Slope=5